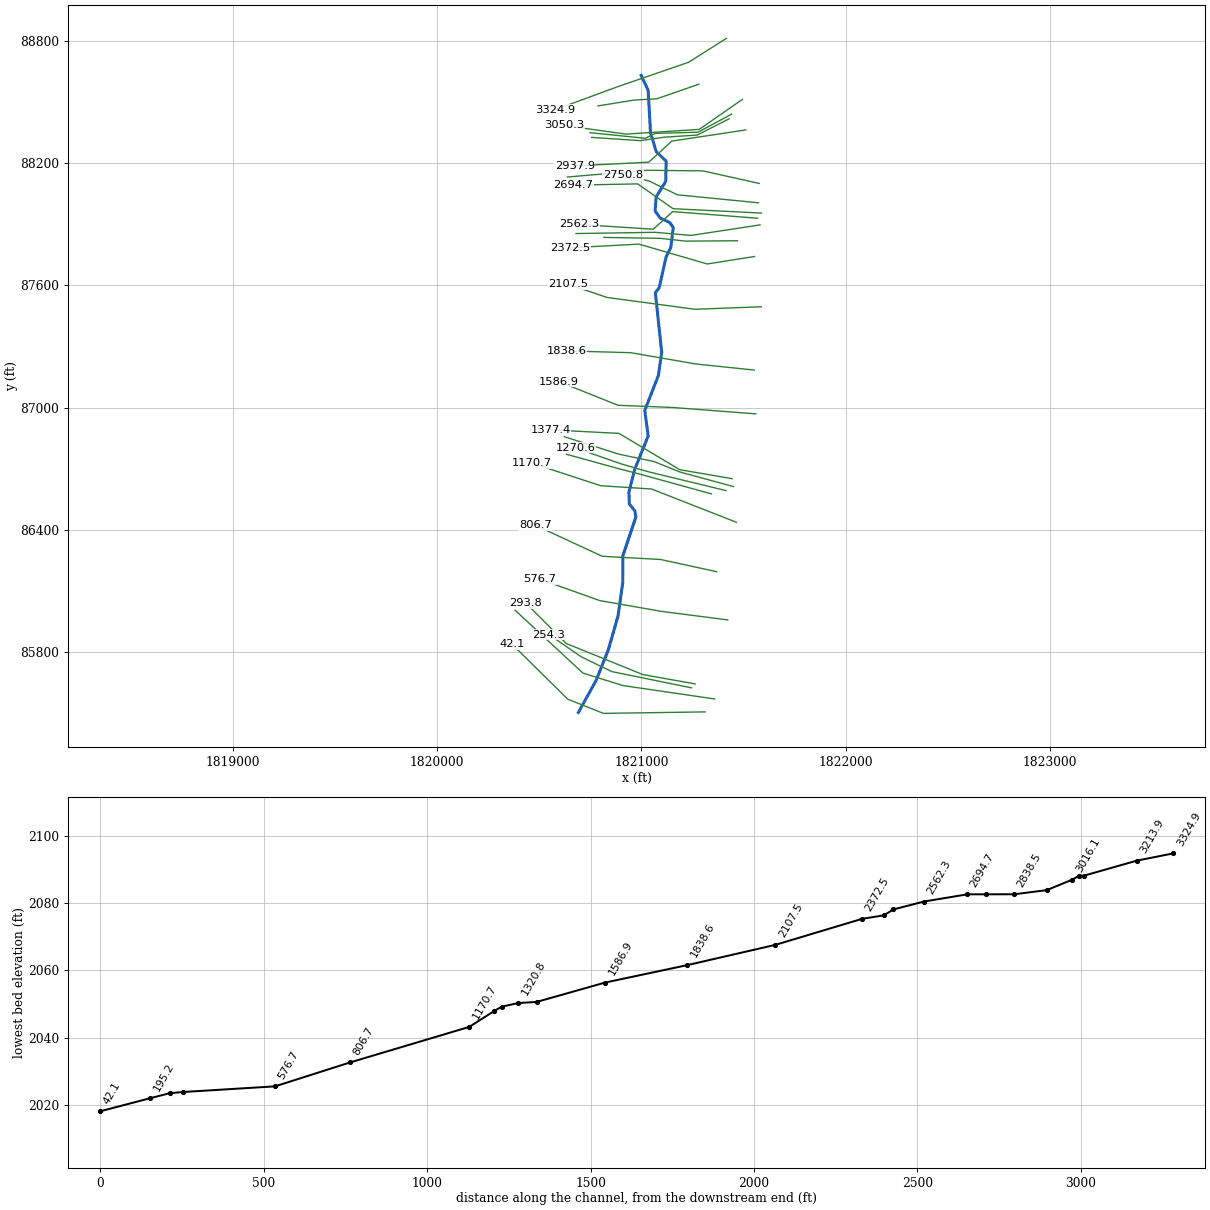
--- Low Gap Branch.prj (project) ---

Proj Title=Low Gap Branch
Current Plan=p01
Default Exp/Contr=0,0
English Units
Geom File=g01
Flow File=f01
Plan File=p01
BEGIN DESCRIPTION:
END DESCRIPTION:
DSS Export Rating Curves= 0
DSS Export Rating Curve Sorted= 0
DSS Export Volume Flow Curves= 0
DXF OffsetX= 0
DXF OffsetY= 0
DXF ScaleX= 0
DXF ScaleY= 0

--- Low Gap Branch.p01 (plan) ---

Plan Title=Floodplain
Program Version=4.00
Geom File=g01
Flow File=f01
K Sum by GR=0
Std Step Tol=0.01
Critical Tol=0.01
Num of Std Step Trials=20
Max Error Tol=0.3
Flow Tol Ratio=0.001
Split Flow NTrial=30
Split Flow Tol=0.02
Split Flow Ratio=0.02
Log Output Level=0
Friction Slope Method=1
Unsteady Friction Slope Method=2
Unsteady Bridges Friction Slope Method=1
Global Log Level=0
CheckData=False
Run HTab=0
Run UNet=0
Run PostProcess=0
UNET Theta=0
UNET Theta Warmup=0
UNET ZTol=0
UNET ZSATol=0
UNET MxIter=0
UNET MaxInSteps=0
UNET DtIC=0
UNET DtMin=0
UNET MaxCRTS=0
UNET WFStab=0
UNET SFStab=0
UNET WFX=0
UNET SFX=0
UNET DSS MLevel=0
UNET DZMax Abort=0
UNET Convert EG Bridges=0
UNET Use Existing IB Tables=0
UNET Froude Limit=0
UNET Froude Power=0
Write IC File=0
Echo Input=False
Echo Output=False
Write Detailed=0

--- Low Gap Branch.f01 (steady flow) ---

Flow Title=NFF Regression Equation
Program Version=4.00
Number of Profiles=1
Profile Names=P100yr
River Rch & RM=Low Gap Branch,Main      ,3324.9
555.5349
River Rch & RM=Low Gap Branch,Main      ,2694.7
562.5055
River Rch & RM=Low Gap Branch,Main      ,2372.5
660.1158
River Rch & RM=Low Gap Branch,Main      ,293.8
701.1411
Boundary for River Rch & Prof#=Low Gap Branch,Main      ,1
Up Type=0
Dn Type=3
Dn Slope=0.018919

--- Low Gap Branch.g01 (geometry) ---

Geom Title=USGS 10m DEM
Program Version=4.00

River Reach=Low Gap Branch  ,Main
Reach XY= 30
     1820998.877        88628.96     1821032.993       88555.312
     1821044.143       88348.966     1821071.888       88256.247
      1821120.74       88208.514     1821118.955       88110.455
     1821072.033       88033.169     1821066.722       87965.238
     1821091.403       87929.651     1821137.322       87908.987
      1821155.69       87883.732     1821143.398       87785.266
     1821120.627        87739.75     1821086.811        87588.13
     1821067.981       87564.305     1821099.132       87271.372
     1821082.996       87158.418     1821016.212       86986.595
     1821032.857       86861.467     1820966.849       86697.308
     1820938.724       86585.955     1820940.446       86527.982
     1820967.727       86494.133     1820972.525       86463.427
     1820908.876       86273.707     1820908.303       86140.543
     1820885.343        85978.68     1820838.276       85813.947
     1820778.582       85663.563     1820691.153       85505.272

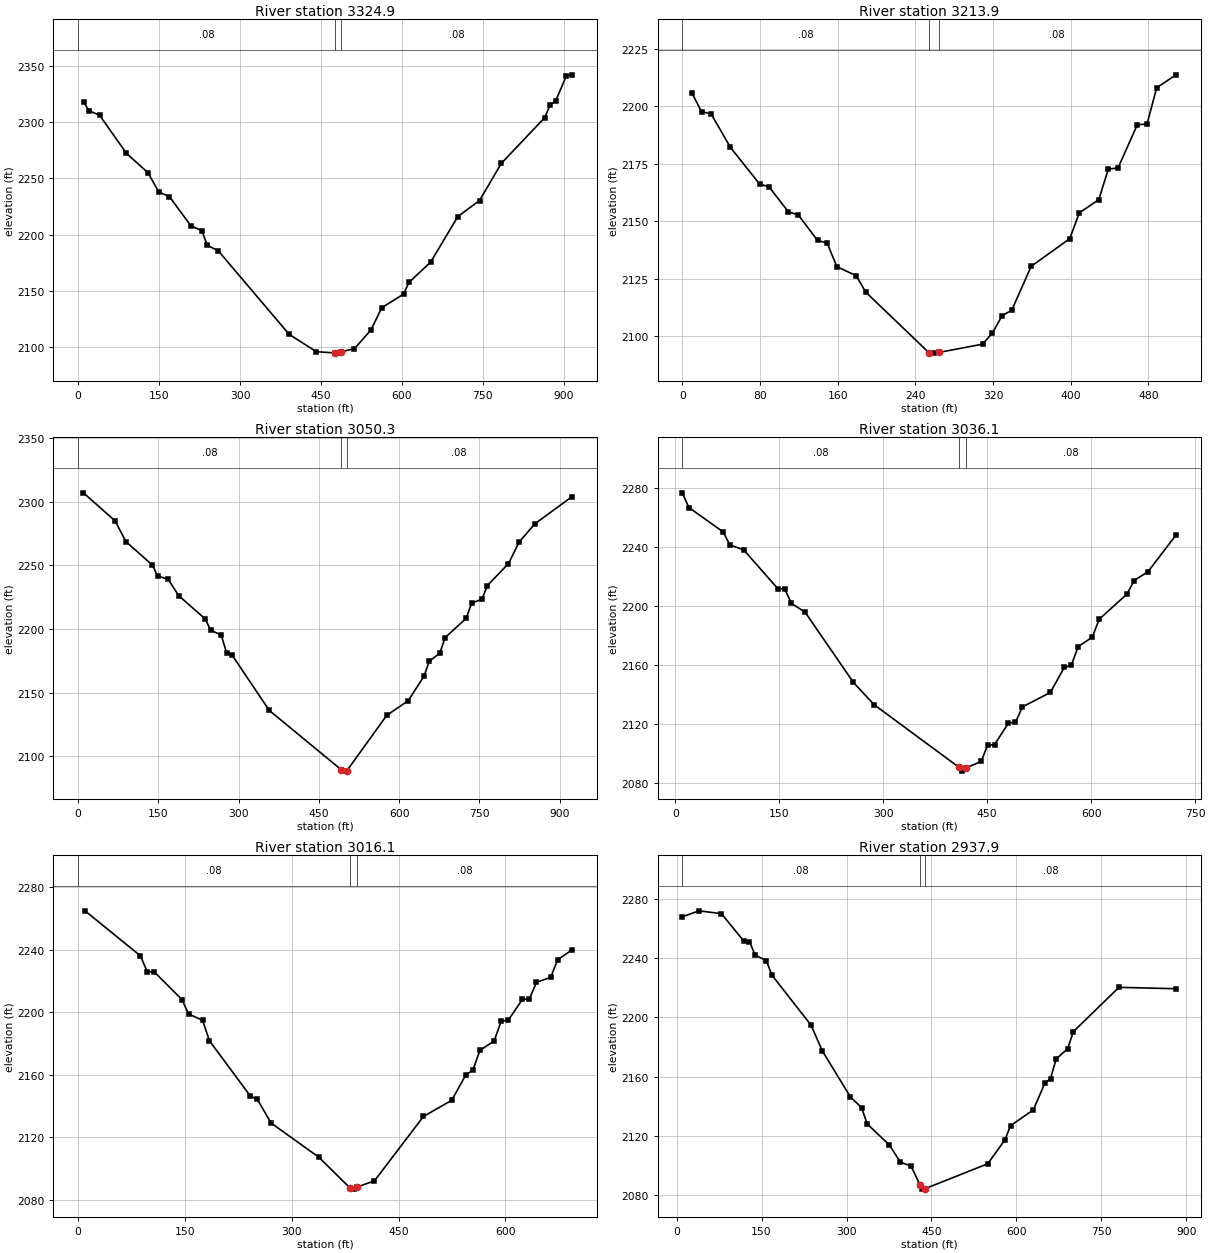
Type RM Length L Ch R = 1 ,3324.9  ,116.7,111,105.3
XS GIS Cut Line= 4
     1821415.675       88811.015     1821230.641         88693.6
     1820886.817       88574.935     1820575.293       88460.193
#Sta/Elev= 30
      10  2318.2    19.9 2310.12    39.8 2306.07    89.6 2272.19   129.5 2254.98
   149.4    2238   169.3  2233.7   209.2 2207.72   229.2 2203.59   239.4 2190.47
   259.6 2185.73   390.9 2111.54   441.4 2096.06   476.8 2094.91   481.8 2094.79
   486.8 2095.89   512.1  2098.8   542.5 2115.27   562.7 2135.15     603  2147.2
     613 2157.54   653.3 2175.71   703.6  2216.1   743.8 2230.32   784.1 2263.27
   864.6 2303.95   874.6 2315.21   884.7 2318.64   904.8 2341.12   914.9 2341.94
#Mann= 3 , 0 , 0
       0     .08       0   476.8    .045       0   486.8     .08       0
Bank Sta=476.8,486.8
XS Rating Curve= 0 ,0
Exp/Cntr=0.3,0.1

Type RM Length L Ch R = 1 ,3213.9  ,163.9,163.5,163.7
XS GIS Cut Line= 4
     1821281.148       88586.221     1821074.398       88514.476
      1820964.08       88508.304     1820787.417        88479.76
#Sta/Elev= 30
     9.9 2205.91    19.9 2197.75    29.8 2196.75    49.7 2182.15    79.6 2166.27
    89.5 2164.97   109.4 2154.07   119.4 2152.86   139.3 2141.69   149.2  2140.6
   159.2 2130.29   179.1 2126.34     189 2119.17     254 2092.84     259 2092.65
     264 2092.94   309.2 2096.55   319.3 2101.37   329.3 2108.95   339.3 2111.34
   359.2 2130.41   398.9 2142.45   408.9 2153.73   428.8 2159.43   438.7 2172.77
   448.6 2173.19   468.5 2192.04   478.5 2192.33   488.4 2208.11   508.3 2213.76
#Mann= 3 , 0 , 0
       0     .08       0     254    .045       0     264     .08       0
Bank Sta=254,264
XS Rating Curve= 0 ,0
Exp/Cntr=0.3,0.1

Type RM Length L Ch R = 1 ,3050.3  ,6.4,14.2,22.3
XS GIS Cut Line= 4
     1821493.765       88511.579     1821282.317       88364.524
     1820923.728       88341.463     1820620.515       88383.786
#Sta/Elev= 30
     9.9 2307.16    69.3 2285.02    89.2 2268.85   138.7 2250.35   148.6 2241.81
   168.4 2239.01   188.2 2226.15   237.7 2207.88   247.7 2199.03   267.5 2195.25
   277.5 2181.24   287.5 2179.74   357.4 2135.88   492.1 2089.17   497.1 2088.13
   502.1 2088.27     577 2132.05   616.9 2143.52   646.5  2162.7   656.4 2174.53
   676.1 2181.05     686 2193.19   725.5 2208.43   735.4 2220.14   755.1 2223.64
     765 2234.17   804.5 2251.47   824.3 2268.36   853.9  2282.8     923 2304.06
#Mann= 3 , 0 , 0
       0     .08       0   492.1    .045       0   502.1     .08       0
Bank Sta=492.1,502.1
XS Rating Curve= 0 ,0
Exp/Cntr=0.3,0.1

Type RM Length L Ch R = 1 ,3036.1  ,25.5,20.1,13.7
XS GIS Cut Line= 5
     1821441.433        88439.47     1821276.552       88350.687
      1821067.76        88345.07     1821018.991       88321.049
     1820748.469       88348.381
#Sta/Elev= 30
     9.9 2276.73    19.7 2266.73      69 2250.23    78.8 2241.37    98.6  2238.1
   147.8 2211.82   157.7 2211.72   167.6 2201.79   187.3 2195.81   256.9 2148.27
   286.7 2133.19   409.3 2090.72   414.3 2088.12   419.3 2090.27   441.4 2094.75
   450.5 2105.65   460.6  2106.1   480.7 2120.71   490.8 2121.16   500.8 2131.65
   541.1 2141.42   561.3 2158.42   571.3 2159.78   581.4 2172.56   601.6 2178.88
   611.6 2191.06   651.9  2208.2     662 2217.31   682.1 2223.29   722.4 2248.13
#Mann= 3 , 0 , 0
     9.9     .08       0   409.3    .045       0   419.3     .08       0
Bank Sta=409.3,419.3
XS Rating Curve= 0 ,0
Exp/Cntr=0.3,0.1

Type RM Length L Ch R = 1 ,3016.1  ,65.8,78.2,90.5
XS GIS Cut Line= 5
      1821428.75       88416.409     1821273.092       88336.851
     1821109.978       88326.144     1820994.242       88309.402
      1820756.54       88325.321
#Sta/Elev= 30
     9.7 2264.89    87.4 2236.17    97.1    2226   106.8 2225.95   145.7 2208.18
   155.4 2198.85   174.8 2194.94   184.4 2181.87   242.1 2146.38   251.7 2144.39
     271 2129.27   338.3 2107.31     382 2087.67     387 2086.99     392 2088.37
   416.2 2092.27     485 2133.42   524.7 2143.79   544.6 2160.02   554.5 2163.11
   564.4 2175.73   584.3 2181.68   594.2 2194.35   604.1 2194.98     624 2208.27
   633.9 2208.68   643.8 2219.17   663.7 2222.38   673.6 2233.66   693.5  2239.9
#Mann= 3 , 0 , 0
       0     .08       0     382    .045       0     392     .08       0
Bank Sta=382,392
XS Rating Curve= 0 ,0
Exp/Cntr=0.3,0.1

Type RM Length L Ch R = 1 ,2937.9  ,115.3,99.4,83.6
XS GIS Cut Line= 4
     1821510.568       88361.947     1821148.488       88307.179
     1821035.909       88203.727     1820673.829       88185.471
#Sta/Elev= 30
     9.9 2267.94    39.6 2272.01    79.2  2270.1   118.8 2251.51   128.7 2251.27
   138.6 2242.12   158.4 2238.35   168.3 2228.57   237.5 2194.64   257.3 2177.29
   306.8 2146.24   326.6 2138.97   336.5 2127.95   375.8 2113.66   394.9 2102.15
     414 2099.39  429.84 2086.69   433.1 2083.87   438.1 2084.09   549.3 2101.02
   579.5 2117.06   589.6 2126.75   629.9 2137.51     650 2155.43   660.1 2158.64
   670.1 2171.87   690.3 2178.72   700.4  2190.3   780.9 2220.29   881.6 2219.34
#Mann= 3 , 0 , 0
     9.9     .08       0  429.84    .045       0   438.1     .08       0
Bank Sta=429.84,438.1
XS Rating Curve= 0 ,0
Exp/Cntr=0.3,0.1

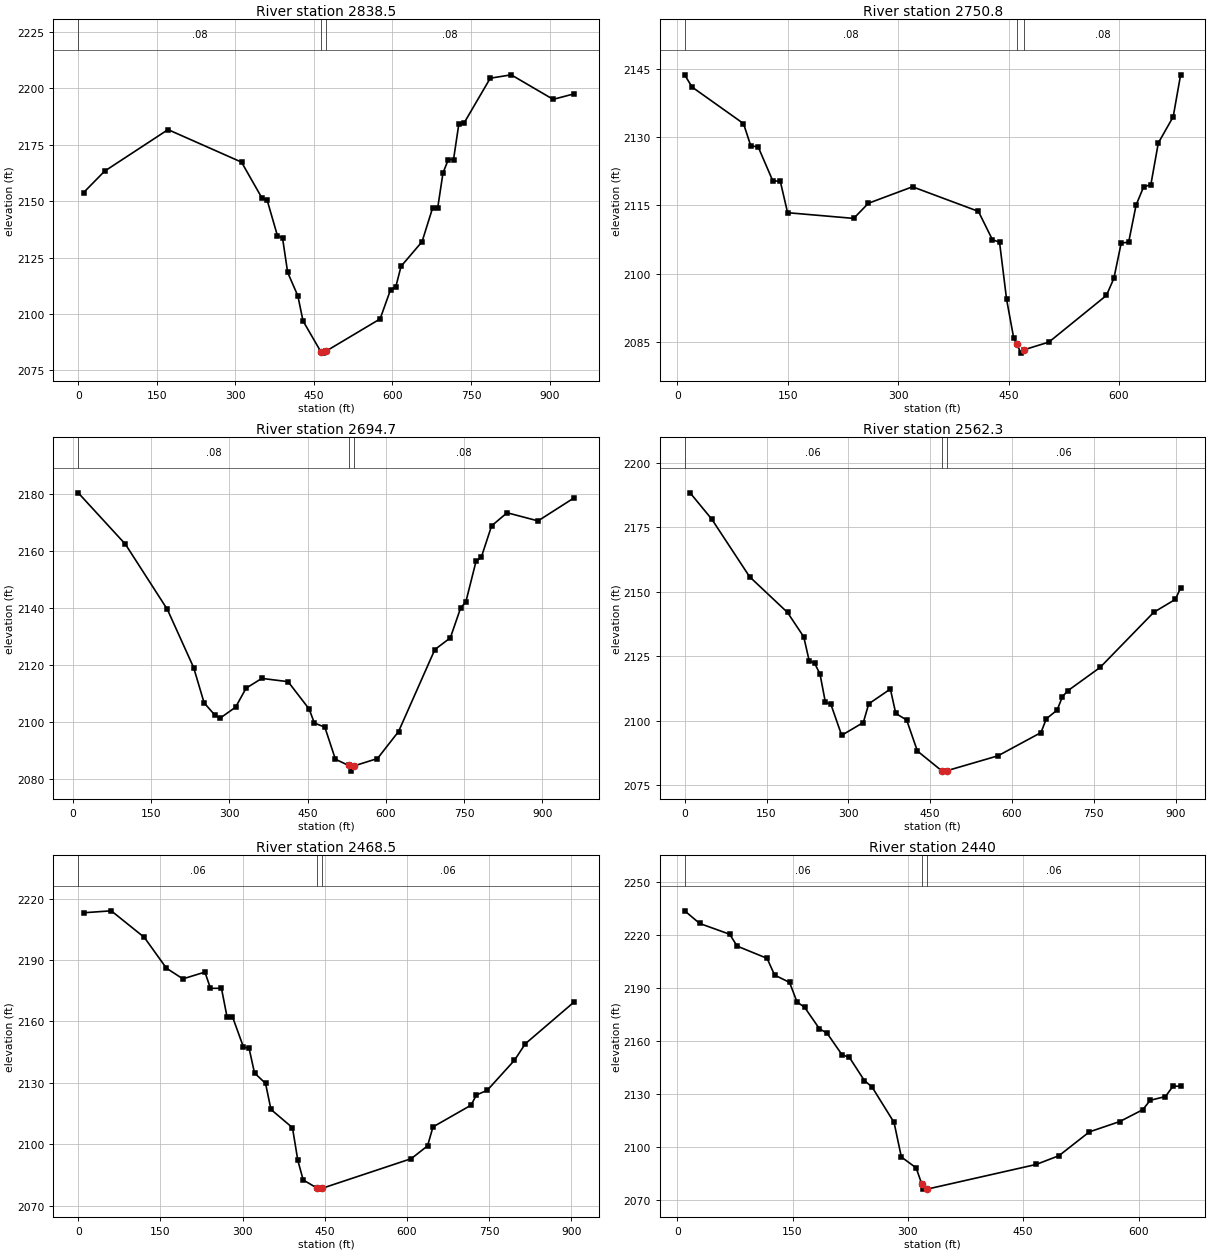
Type RM Length L Ch R = 1 ,2838.5  ,96.7,87.7,78.7
XS GIS Cut Line= 4
     1821576.313       88099.507     1821300.622        88161.13
     1821026.781       88164.172     1820637.643       88131.123
#Sta/Elev= 30
    10.1 2153.75    50.4 2163.28   171.5 2181.69   311.8 2167.28     351 2151.29
   360.7 2150.46   380.3 2134.73   390.1 2133.68   399.9 2118.41   419.4 2107.98
   429.2 2096.92   463.3 2083.25   468.3 2082.64   473.3 2083.53   576.4  2097.8
   596.4 2110.78   606.4 2112.06   616.4 2121.12   656.5 2132.02   676.5 2146.86
   686.5 2147.17   696.5 2162.53   706.6 2168.38   716.6 2168.43   726.6 2184.01
   736.6 2184.57   786.7 2204.47   826.7 2205.97   906.8  2195.1   946.9 2197.55
#Mann= 3 , 0 , 0
       0     .08       0   463.3    .045       0   473.3     .08       0
Bank Sta=463.3,473.3
XS Rating Curve= 0 ,0
Exp/Cntr=0.3,0.1

Type RM Length L Ch R = 1 ,2750.8  ,59.4,56.1,52.9
XS GIS Cut Line= 4
     1821572.535       88004.611     1821175.086       88043.984
     1821037.534        88111.56     1820909.612       88139.812
#Sta/Elev= 30
      10 2143.64      20 2140.97    89.9 2132.96    99.8 2128.08   109.8 2127.86
   129.8 2120.36   139.8 2120.36   149.8 2113.42   239.6 2112.17   259.6 2115.49
   319.5  2119.1     409 2113.71   428.1 2107.48   437.7 2106.97   447.3 2094.41
   456.9 2085.99   461.4 2084.72   466.4 2082.63   471.4 2083.39   504.8 2085.05
   582.9 2095.28     593 2099.01     603 2106.77   613.1 2106.95   623.2 2115.08
   633.3 2119.03   643.3  2119.6   653.4 2128.71   673.6 2134.45   683.7 2143.65
#Mann= 3 , 0 , 0
      10     .08       0   461.4    .045       0   471.4     .08       0
Bank Sta=461.4,471.4
XS Rating Curve= 0 ,0
Exp/Cntr=0.3,0.1

Type RM Length L Ch R = 1 ,2694.7  ,105,132.4,159.7
XS GIS Cut Line= 4
     1821587.051       87954.323      1821154.99       87975.622
     1820981.557        88097.33     1820665.118       88091.244
#Sta/Elev= 30
    10.1 2180.28   100.6 2162.24   181.1 2139.34   231.4 2118.97   251.5 2106.59
   271.6 2102.38   281.7 2101.15   311.9 2105.07     332 2111.73   362.2 2115.16
   412.5 2114.01   452.8 2104.43   462.9  2099.5     483 2098.04   503.2  2086.8
   528.5 2084.62   533.5 2082.62   538.5 2084.42   583.9 2087.04   624.3 2096.51
   693.9 2125.28   723.6 2129.39   743.4 2139.92   753.3 2141.98     773 2156.35
   782.9 2157.63   802.7 2168.68   832.4 2173.29   891.7 2170.43     961 2178.52
#Mann= 3 , 0 , 0
    10.1     .08       0   528.5    .045       0   538.5     .08       0
Bank Sta=528.5,538.5
XS Rating Curve= 0 ,0
Exp/Cntr=0.3,0.1

Type RM Length L Ch R = 1 ,2562.3  ,110.9,93.8,76.7
XS GIS Cut Line= 4
     1821568.174       87929.014     1821152.661       87961.484
     1821058.092       87875.138     1820694.453       87898.485
#Sta/Elev= 30
     9.9 2188.36    49.6 2178.17   119.1 2155.81   188.5 2141.99   218.3 2132.52
   228.2  2123.3   238.2 2122.29   248.1 2118.11     258 2107.09   267.9 2106.48
   287.8 2094.36   327.5 2099.33   337.4 2106.56   377.1  2112.3     387 2102.82
   406.9 2100.32   426.6 2088.28   470.9 2080.67   475.9 2080.48   480.9 2080.65
   574.4 2086.42   653.2 2095.42     663 2100.78   682.7 2104.11   692.6 2109.35
   702.4 2111.64   761.5 2120.66     860 2142.06   899.4 2147.03   909.2 2151.47
#Mann= 3 , 0 , 0
       0     .06       0   470.9    .045       0   480.9     .06       0
Bank Sta=470.9,480.9
XS Rating Curve= 0 ,0
Exp/Cntr=0.3,0.1

Type RM Length L Ch R = 1 ,2468.5  ,29,28.5,28
XS GIS Cut Line= 4
     1821580.549       87896.416     1821242.527       87844.695
     1821066.336       87859.904     1820679.915       87853.819
#Sta/Elev= 30
    10.1 2213.09    60.3 2214.03   120.7 2201.05   160.9 2186.05   191.1  2180.8
   231.3 2184.11   241.4 2176.19   261.5 2176.19   271.6 2162.33   281.6  2162.3
   301.7 2147.45   311.8 2147.04   321.8 2134.85     342 2129.74   351.8 2117.04
   391.1 2108.12   400.9 2092.13   410.7 2082.58   435.2 2078.76   440.2 2078.12
   445.2 2078.52     608    2093   637.7 2099.26   647.6  2108.5     717  2119.1
   726.9  2124.1   746.7 2126.39   796.3 2141.04   816.1 2149.09   905.3 2169.53
#Mann= 3 , 0 , 0
       0     .06       0   435.2    .045       0   445.2     .06       0
Bank Sta=435.2,445.2
XS Rating Curve= 0 ,0
Exp/Cntr=0.3,0.1

Type RM Length L Ch R = 1 ,2440    ,71,67.5,63.9
XS GIS Cut Line= 4
     1821469.986       87818.518     1821216.797       87816.697
     1821092.935       87830.358     1820816.066       87834.912
#Sta/Elev= 30
     9.7  2233.7    29.2 2226.56    68.2 2220.46    77.9 2213.77   116.9 2206.83
   126.6  2197.4   146.1 2193.24   155.8 2182.17   165.6 2179.21     185 2167.01
   194.8 2164.57   214.2 2152.42     224  2150.8   243.5 2137.71   253.2 2134.23
     282 2114.08   291.5 2094.54   310.7 2088.42  318.24 2079.08   320.3 2076.39
   325.3 2076.42   466.8 2090.33   496.5 2095.29     536 2108.74   575.6  2114.6
   605.3 2121.24   615.2 2126.61   634.9 2128.71   644.8 2134.56   654.7 2134.57
#Mann= 3 , 0 , 0
     9.7     .06       0  318.24    .045       0   325.3     .06       0
Bank Sta=318.24,325.3
XS Rating Curve= 0 ,0
Exp/Cntr=0.3,0.1

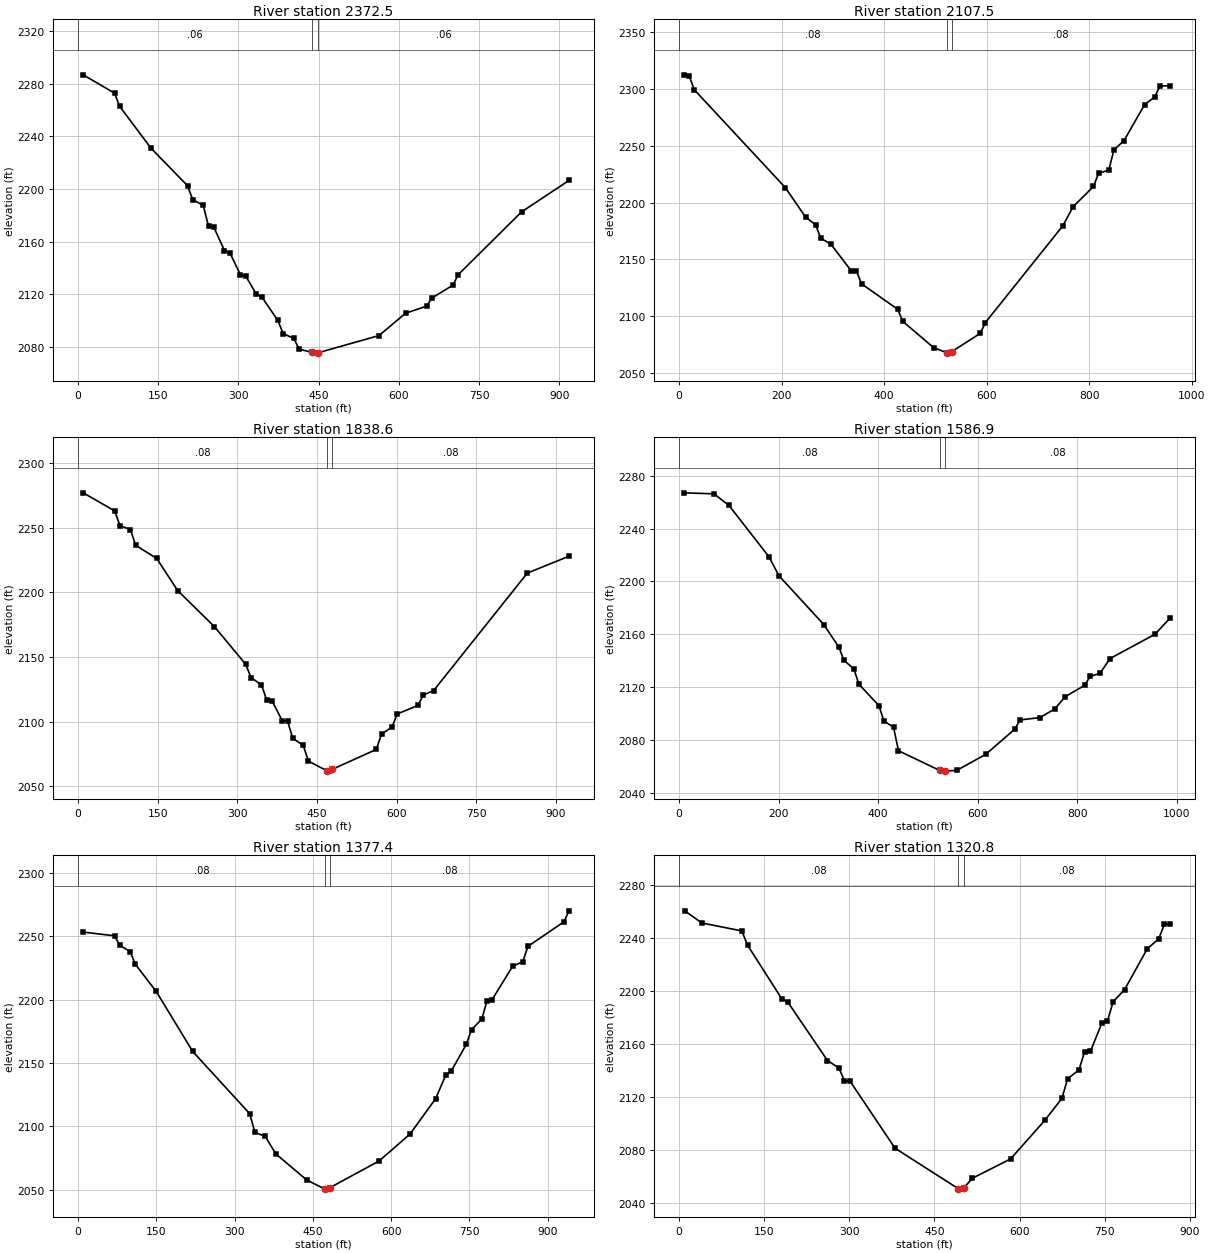
Type RM Length L Ch R = 1 ,2372.5  ,262.2,265.1,268
XS GIS Cut Line= 4
     1821553.165       87741.239     1821321.921       87704.727
     1820987.226       87802.093     1820652.531       87783.837
#Sta/Elev= 30
     9.8 2286.72    68.3 2272.81      78 2262.74   136.6 2230.96   204.8 2202.47
   214.6 2191.84   234.1 2187.59   244.1 2171.57     254 2170.94   273.9 2153.21
   283.9 2151.55   303.8 2134.81   313.8 2133.73   333.7 2119.88   343.7 2117.94
   373.5 2100.23   383.5 2090.19   403.4 2086.48   413.4 2078.37   438.3 2075.82
   443.3 2075.32   448.3 2075.53   562.8 2088.67   612.3 2105.61   651.7 2111.01
   661.5 2117.18     701 2126.94   710.8 2134.91   829.1 2182.58   917.9 2206.49
#Mann= 3 , 0 , 0
       0     .06       0   438.3    .045       0   448.3     .06       0
Bank Sta=438.3,448.3
XS Rating Curve= 0 ,0
Exp/Cntr=0.3,0.1

Type RM Length L Ch R = 1 ,2107.5  ,269.5,268.8,268.1
XS GIS Cut Line= 4
     1821586.635       87494.782     1821261.067       87482.611
     1820832.049       87540.422     1820643.403       87604.319
#Sta/Elev= 30
     9.9 2312.27    19.7 2311.48    29.6 2299.23   207.3 2213.14   246.8 2187.22
   266.6 2180.29   276.4 2168.58   296.2 2163.35   335.9 2139.96   345.9 2139.97
     356 2128.49   426.5 2106.15   436.5 2095.51   496.9 2072.31   522.1 2068.04
   527.1 2067.59   532.1 2068.94   587.5 2084.93   597.6 2094.47   748.6  2179.5
   768.6 2196.21   808.5 2214.13   818.4  2225.7   838.4 2228.59   848.3  2246.2
   868.2 2254.52   908.1 2286.08     928 2292.77   937.9 2302.26   957.9 2302.85
#Mann= 3 , 0 , 0
       0     .08       0   522.1    .045       0   532.1     .08       0
Bank Sta=522.1,532.1
XS Rating Curve= 0 ,0
Exp/Cntr=0.3,0.1

Type RM Length L Ch R = 1 ,1838.6  ,249.1,251.7,254.4
XS GIS Cut Line= 4
     1821552.491       87184.557     1821267.395       87214.144
     1820947.671       87269.623     1820634.041       87278.506
#Sta/Elev= 30
     9.9 2277.13    69.2 2263.09    79.1 2251.66    98.8 2248.72   108.7 2236.47
   148.3 2226.32   187.8 2201.42     257 2173.48   316.1 2144.23     326 2133.96
   345.6 2128.48   355.5 2116.61   365.3 2116.16     385 2100.45   394.8 2100.34
   404.6 2086.95   424.3 2081.61   434.1 2069.33   468.5 2061.94   473.5 2061.58
   478.5 2062.87     562 2078.42   571.8 2090.33   591.5 2095.66   601.3 2105.85
   640.5 2112.47   650.3 2120.46     670 2124.01   846.4 2214.98   924.9 2228.03
#Mann= 3 , 0 , 0
       0     .08       0   468.5    .045       0   478.5     .08       0
Bank Sta=468.5,478.5
XS Rating Curve= 0 ,0
Exp/Cntr=0.3,0.1

Type RM Length L Ch R = 1 ,1586.9  ,219.8,209.5,199.3
XS GIS Cut Line= 4
     1821559.209        86969.77     1821148.776       87001.341
     1820885.678       87011.865     1820596.271       87127.628
#Sta/Elev= 30
      10 2267.04    70.3 2266.27   100.4 2257.46   180.7 2218.61   200.8 2204.24
   291.2 2167.19   321.3 2150.16   331.3 2140.26   351.4  2133.7   361.4 2122.16
   401.6 2105.99   411.6 2094.43   431.1 2089.51   440.9 2071.83   523.7 2056.92
   528.7 2056.39   533.7 2056.46   557.9 2056.92   616.4 2069.11     675 2088.29
     685  2095.1   725.2 2096.92   755.4 2103.53   775.5 2112.65   815.7 2121.46
   825.8 2128.12   845.9 2130.38     866 2141.61   956.5 2160.03   986.7 2172.27
#Mann= 3 , 0 , 0
       0     .08       0   523.7    .045       0   533.7     .08       0
Bank Sta=523.7,533.7
XS Rating Curve= 0 ,0
Exp/Cntr=0.3,0.1

Type RM Length L Ch R = 1 ,1377.4  ,49.9,56.6,63.4
XS GIS Cut Line= 4
     1821443.628       86651.959     1821187.533       86696.018
      1820889.86       86874.074     1820556.155       86891.176
#Sta/Elev= 30
      10 2253.21      70 2250.28      80 2242.84    99.9 2237.86   109.9 2227.87
   149.9 2206.42   219.9 2159.12   329.2    2110   339.1 2095.37     359 2092.14
   378.8  2078.5   438.2 2057.89   472.9 2050.71   477.9 2050.63   482.9  2051.8
     577 2072.81   636.2 2094.01   685.3 2121.91     705  2140.7   714.8 2143.38
   744.3 2164.88   754.1 2176.27   773.8 2184.64   783.6 2198.88   793.4 2199.84
   832.8 2226.22   852.4 2229.91   862.2 2241.96     931 2261.25   940.9 2269.97
#Mann= 3 , 0 , 0
       0     .08       0   472.9    .045       0   482.9     .08       0
Bank Sta=472.9,482.9
XS Rating Curve= 0 ,0
Exp/Cntr=0.3,0.1

Type RM Length L Ch R = 1 ,1320.8  ,51.8,50.2,48.6
XS GIS Cut Line= 5
     1821450.766       86613.096     1821188.765        86684.45
     1821060.134       86736.283     1820889.941       86771.942
     1820622.496       86857.849
#Sta/Elev= 30
    10.1 2260.57    40.2 2251.38   110.6  2245.4   120.7 2234.57     181 2194.08
   191.1 2191.92   261.5 2147.46   281.4 2141.87   291.4 2132.24   301.3 2131.84
   380.5 2081.19   492.2 2050.56   497.2 2050.29   502.2 2051.38   516.5 2058.46
   584.1 2073.13   644.3 2102.27   674.4 2118.81   684.4 2133.57   704.5 2140.39
   714.5 2154.24   724.6 2154.29   744.6 2175.53   754.7 2177.31   764.7 2191.87
   784.8 2201.01   824.9 2231.96     845 2239.42     855  2250.5     865 2250.32
#Mann= 3 , 0 , 0
       0     .08       0   492.2    .045       0   502.2     .08       0
Bank Sta=492.2,502.2
XS Rating Curve= 0 ,0
Exp/Cntr=0.3,0.1

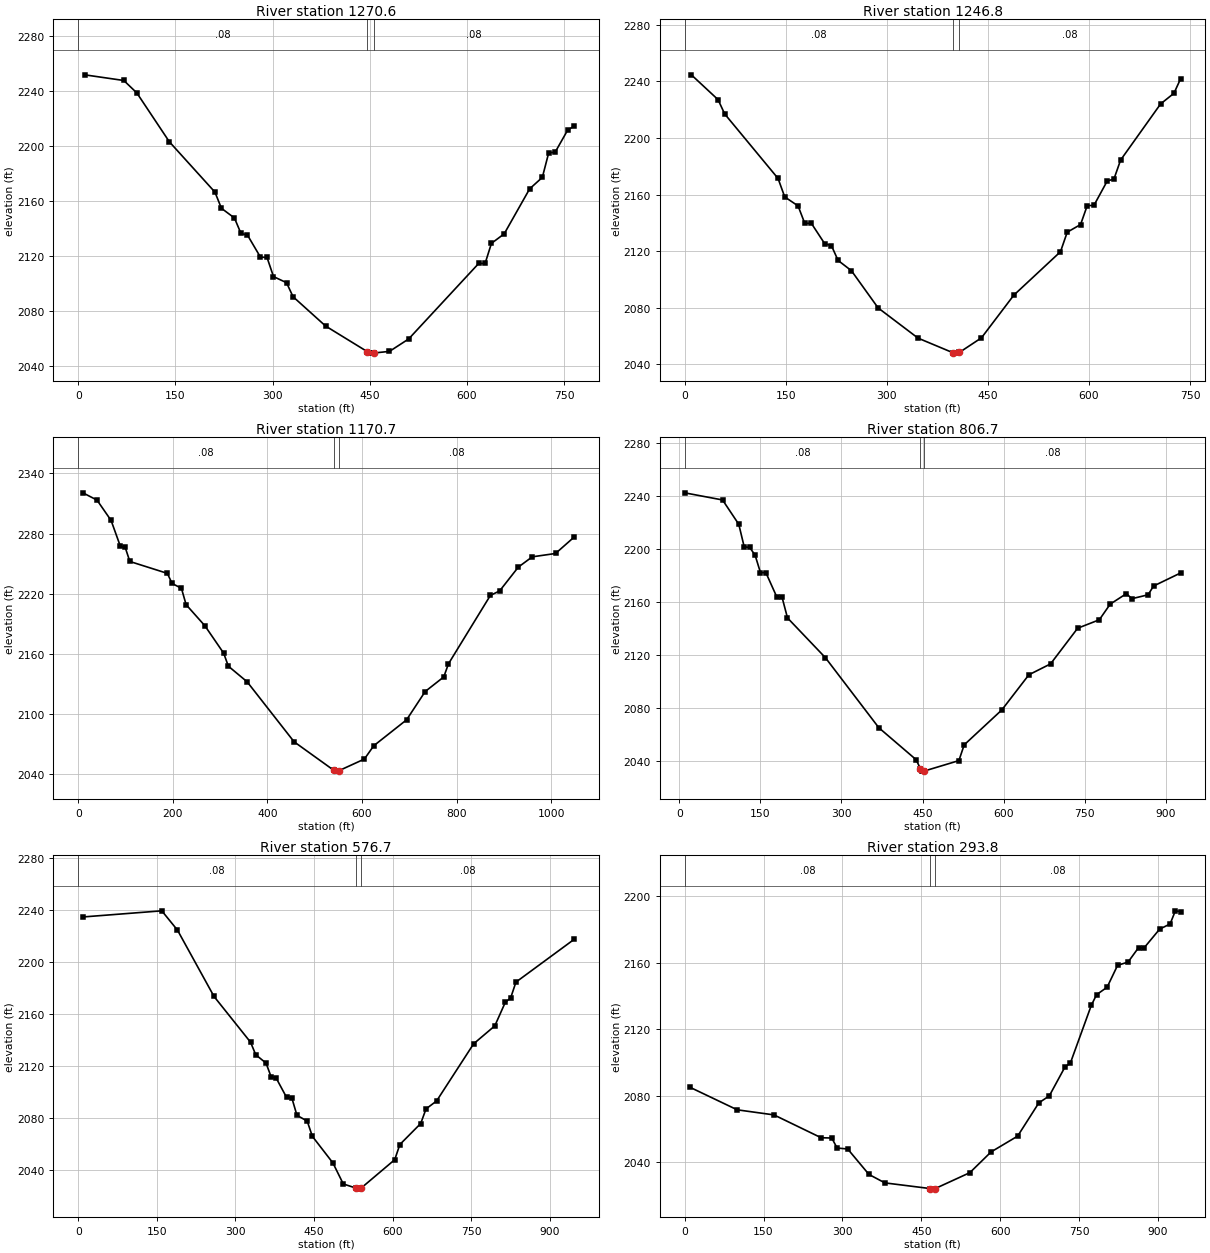
Type RM Length L Ch R = 1 ,1270.6  ,23.2,23.8,24.4
XS GIS Cut Line= 4
     1821413.486       86593.646     1821032.579       86686.036
     1820900.137       86724.718     1820677.606       86802.739
#Sta/Elev= 30
      10 2251.53    70.4 2247.41    90.5 2238.38   140.7 2202.87   211.1 2166.26
   221.1 2154.52   241.2 2147.47   251.3 2136.21   261.3 2135.05   281.4 2118.98
   291.5 2118.81   301.5 2104.86   321.6 2100.44   331.7 2090.23   381.9 2068.94
   446.1 2050.38   451.1 2049.23   456.1  2049.3   480.6  2050.5   510.2 2059.53
   618.4 2114.45   628.2 2114.39     638 2129.04   657.7 2135.94     697 2168.66
   716.6    2177   726.4 2194.85   736.3 2195.25   755.9 2211.51   765.7 2214.15
#Mann= 3 , 0 , 0
       0     .08       0   446.1    .045       0   456.1     .08       0
Bank Sta=446.1,456.1
XS Rating Curve= 0 ,0
Exp/Cntr=0.3,0.1

Type RM Length L Ch R = 1 ,1246.8  ,72.3,76.1,79.9
XS GIS Cut Line= 4
     1821342.167       86577.437     1821008.266       86669.827
     1820889.941       86700.624     1820632.222       86771.942
#Sta/Elev= 30
     9.9 2244.65    49.5 2227.12    59.4 2216.98   138.6 2171.38   148.5 2158.33
   168.3 2151.97   178.2 2139.69   188.1 2139.61   207.9 2125.21   217.8 2123.91
   227.7 2113.42   247.5 2106.16   287.1 2079.87   346.4 2058.49   397.9 2048.23
   402.9 2047.89   407.9 2048.44   440.5 2058.71   488.5 2088.86   557.8  2119.6
   567.8  2133.4   587.6  2138.8   597.5  2152.2   607.4 2152.31   627.2 2169.63
   637.1 2170.92     647 2184.38   706.4 2224.08   726.2 2231.61   736.1 2241.89
#Mann= 3 , 0 , 0
       0     .08       0   397.9    .045       0   407.9     .08       0
Bank Sta=397.9,407.9
XS Rating Curve= 0 ,0
Exp/Cntr=0.3,0.1

Type RM Length L Ch R = 1 ,1170.7  ,363.6,363.9,364.3
XS GIS Cut Line= 4
     1821464.494       86438.312     1821048.799       86601.433
     1820801.487       86617.219     1820464.722        86727.72
#Sta/Elev= 30
     9.9 2320.61    39.7 2313.38    69.5 2293.11    89.3 2267.11    99.2 2266.41
   109.2 2252.18   188.5 2240.33   198.5 2230.28   218.3 2225.42   228.2 2209.11
   267.9 2188.08   307.6 2160.77   317.5 2147.81   357.2 2132.25   456.5 2072.45
   540.7 2043.95   545.7 2043.19   550.7 2043.48   605.2 2055.24     625 2068.48
   694.4 2094.31   733.8 2122.56   773.1 2137.11     783 2150.17   871.6 2218.32
   891.3 2222.88   930.7 2246.55   960.2 2256.81  1009.4 2260.14  1048.8 2276.51
#Mann= 3 , 0 , 0
       0     .08       0   540.7    .045       0   550.7     .08       0
Bank Sta=540.7,550.7
XS Rating Curve= 0 ,0
Exp/Cntr=0.3,0.1

Type RM Length L Ch R = 1 ,806.7   ,232.4,230.1,227.7
XS GIS Cut Line= 4
     1821367.479       86196.043     1821093.566       86255.704
     1820807.708       86271.623     1820480.486       86423.694
#Sta/Elev= 30
      10 2242.35    80.1 2236.97   110.1 2218.64   120.1 2201.65   130.2 2201.18
   140.2 2195.46   150.2 2182.24   160.2 2182.24   180.2 2164.08   190.2  2163.6
   200.2 2148.09   270.3 2118.15   369.2 2065.34   438.3 2041.23  445.91 2034.59
   448.2 2032.65   453.2 2032.71   517.3 2040.58   527.1 2052.44   596.7 2078.75
   646.8 2105.25   686.9 2113.46     737 2140.32   777.1  2146.7   797.2 2158.47
   827.2 2166.39   837.3 2162.58   867.3 2165.51   877.4 2172.11   927.5 2181.97
#Mann= 3 , 0 , 0
      10     .08       0  445.91    .045       0   453.2     .08       0
Bank Sta=445.91,453.2
XS Rating Curve= 0 ,0
Exp/Cntr=0.3,0.1

Type RM Length L Ch R = 1 ,576.7   ,287.4,282.8,278.3
XS GIS Cut Line= 4
     1821422.398       85959.474     1821096.157        86001.57
     1820796.225       86054.189     1820501.556       86159.428
#Sta/Elev= 30
      10  2234.4   159.5 2239.08   189.4 2224.28   259.2 2173.35   328.9 2138.24
   338.8 2128.61   358.4 2122.25   368.2 2111.63   378.1 2110.48   397.7 2095.84
   407.5 2095.69   417.4 2082.18     437  2077.7   446.8 2066.04   486.1 2045.59
   505.8 2029.49   530.2 2026.29   535.2 2025.52   540.2 2026.43     604 2048.11
   613.8 2059.76   653.6 2075.88   663.7 2087.07   683.9 2093.18   754.6 2137.05
     795 2150.81   815.1 2168.96   825.2  2172.2   835.3 2184.37   946.4  2217.2
#Mann= 3 , 0 , 0
       0     .08       0   530.2    .045       0   540.2     .08       0
Bank Sta=530.2,540.2
XS Rating Curve= 0 ,0
Exp/Cntr=0.3,0.1

Type RM Length L Ch R = 1 ,293.8   ,40.8,39.5,38.2
XS GIS Cut Line= 4
     1821262.521       85645.743     1821006.936       85691.384
     1820632.686       85843.518     1820434.911       86041.292
#Sta/Elev= 30
      10 2085.07    99.9 2071.51   169.8 2068.46   259.6 2054.72   279.8 2054.56
   289.9 2048.55   310.1 2047.95   350.5 2032.66   380.8 2027.58   466.7 2024.18
   471.7 2023.83   476.7  2024.2   542.4 2033.73   582.8  2046.2   633.3  2055.7
   673.6 2075.67   693.6 2079.93   723.6 2097.42   733.5 2099.53   773.5  2134.4
   783.5 2140.74   803.5 2145.22   823.4 2158.37   843.4 2160.35   863.4 2169.06
   873.4 2168.71   903.4 2180.13   923.3 2183.25   933.3 2191.14   943.3 2190.68
#Mann= 3 , 0 , 0
       0     .08       0   466.7    .045       0   476.7     .08       0
Bank Sta=466.7,476.7
XS Rating Curve= 0 ,0
Exp/Cntr=0.3,0.1

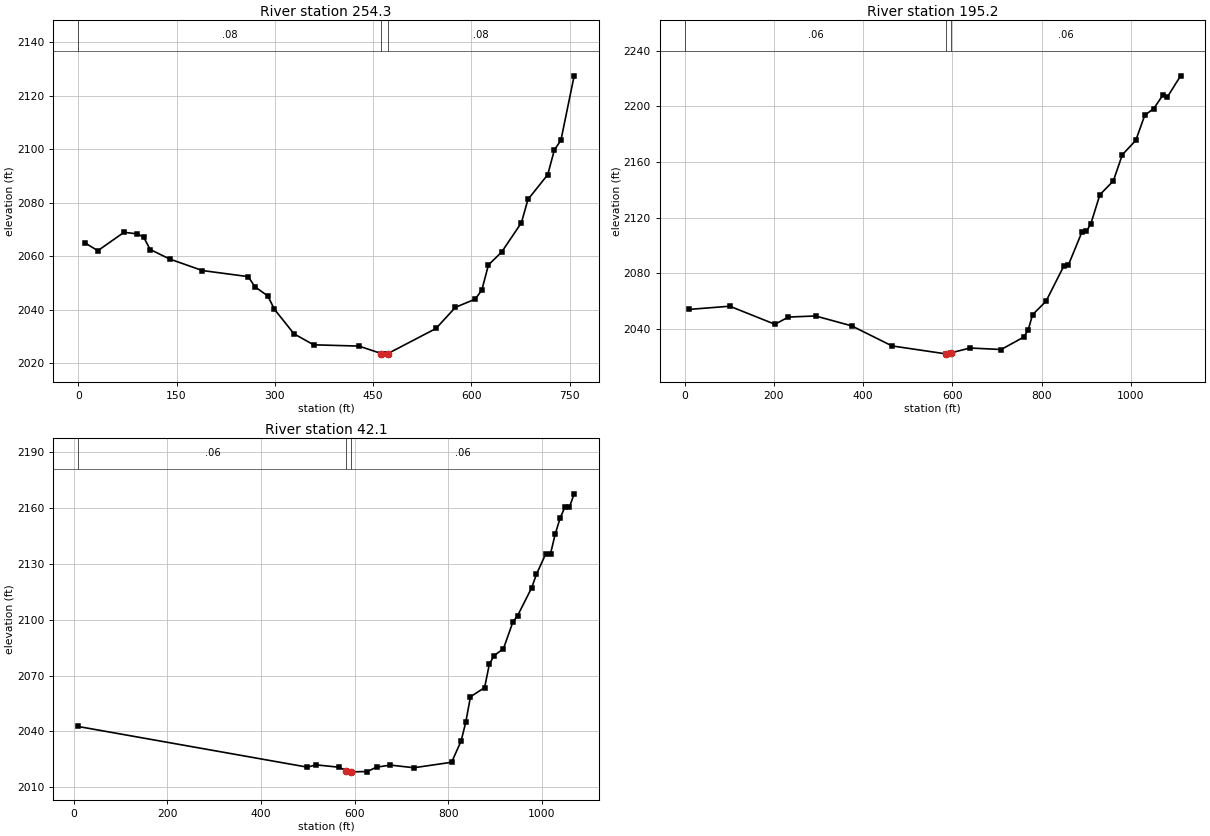
Type RM Length L Ch R = 1 ,254.3   ,56.1,59.1,62.1
XS GIS Cut Line= 4
     1821245.435       85626.229     1820854.368       85706.187
     1820704.629       85778.876     1820547.621       85887.909
#Sta/Elev= 30
      10 2065.08    29.9  2062.1    69.9 2068.98    89.8  2068.4    99.8  2067.2
   109.8 2062.55   139.7 2058.98   189.6 2054.69   259.5 2052.42   269.4 2048.69
   289.4 2045.18   299.4 2040.23   329.3 2031.06   359.2 2026.96   428.5 2026.48
   462.7 2023.69   467.7 2023.48   472.7 2023.71     546 2033.06   575.7 2040.98
   605.8 2044.01   615.9 2047.39     626 2056.79   646.1 2061.58   676.3 2072.55
   686.3 2081.23   716.5 2090.51   726.6 2099.73   736.6 2103.35   756.8 2127.41
#Mann= 3 , 0 , 0
       0     .08       0   462.7    .045       0   472.7     .08       0
Bank Sta=462.7,472.7
XS Rating Curve= 0 ,0
Exp/Cntr=0.3,0.1

Type RM Length L Ch R = 1 ,195.2   ,154.6,153.1,151.5
XS GIS Cut Line= 4
     1821358.433       85571.806     1820908.158        85637.86
     1820713.352       85698.918     1820381.732        86006.91
#Sta/Elev= 30
    10.1 2054.15   101.1 2056.45   202.3 2043.47   232.6 2048.65   293.3 2049.44
   374.2 2042.35   464.8 2027.91   586.2 2022.16   591.2 2022.01   596.2 2022.88
   639.8  2026.4   709.5 2025.33   759.8 2034.19   769.9 2039.15   779.9 2050.37
   810.1 2060.03   850.3 2085.56   860.4 2086.22   890.6 2109.78   900.6  2110.2
   910.7 2115.89   930.8  2136.6     961 2146.52   981.1 2165.32  1011.3 2175.64
  1031.4  2193.7  1051.5 2198.46  1071.6 2207.99  1081.7 2206.64  1111.8 2222.04
#Mann= 3 , 0 , 0
       0     .06       0   586.2    .045       0   596.2     .06       0
Bank Sta=586.2,596.2
XS Rating Curve= 0 ,0
Exp/Cntr=0.3,0.1

Type RM Length L Ch R = 1 ,42.1    ,58.7,42.1,38.9
XS GIS Cut Line= 4
     1821312.308       85508.473     1820813.662       85501.204
     1820639.209       85570.986     1820367.328       85839.849
#Sta/Elev= 30
      10 2042.64   498.7 2020.82   518.5 2022.01   567.9 2020.73   582.7 2018.67
   587.7 2018.12   592.7 2018.26   627.3 2018.45     647 2020.79   676.7  2021.9
   726.8 2020.48   807.3 2023.42   827.5 2034.79   837.5 2044.85   847.6 2058.63
   877.8 2063.54   887.8 2075.99   897.9 2080.73     918  2084.4   938.2 2098.83
   948.2 2102.16   978.4 2117.24   988.5 2124.45  1008.6 2135.54  1018.6 2135.56
  1028.7 2146.17  1038.8 2154.43  1048.8 2160.33  1058.9 2160.46    1069 2167.67
#Mann= 3 , 0 , 0
      10     .06       0   582.7    .045       0   592.7     .06       0
Bank Sta=582.7,592.7
XS Rating Curve= 0 ,0
Exp/Cntr=0.3,0.1

Chan Stop Cuts=-1
Use User Specified Reach Order=0